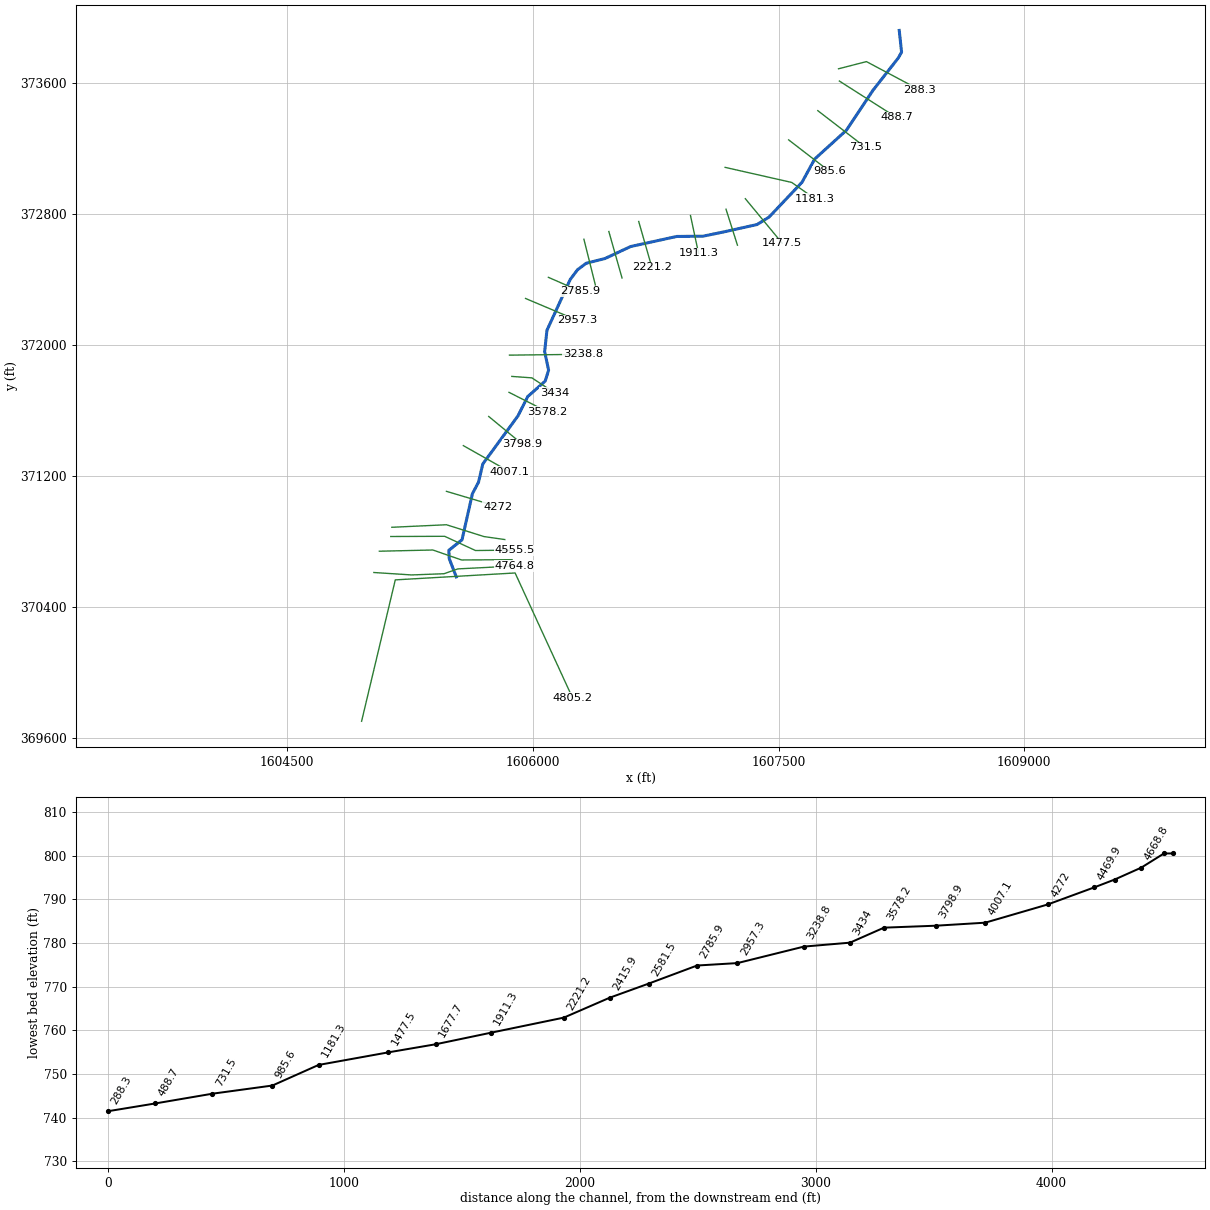
--- PARKERBR.prj (project) ---

Proj Title=PARKERBR
Current Plan=p01
Default Exp/Contr=0,0
English Units
Geom File=g01
Flow File=f01
Plan File=p01
BEGIN DESCRIPTION:
END DESCRIPTION:
DSS Export Rating Curves= 0
DSS Export Rating Curve Sorted= 0
DSS Export Volume Flow Curves= 0
DXF OffsetX= 0
DXF OffsetY= 0
DXF ScaleX= 0
DXF ScaleY= 0

--- PARKERBR.p01 (plan) ---

Plan Title=Floodplain
Program Version=4.00
Geom File=g01
Flow File=f01
K Sum by GR=0
Std Step Tol=0.01
Critical Tol=0.01
Num of Std Step Trials=20
Max Error Tol=0.3
Flow Tol Ratio=0.001
Split Flow NTrial=30
Split Flow Tol=0.02
Split Flow Ratio=0.02
Log Output Level=0
Friction Slope Method=1
Unsteady Friction Slope Method=2
Unsteady Bridges Friction Slope Method=1
Global Log Level=0
CheckData=False
Run HTab=0
Run UNet=0
Run PostProcess=0
UNET Theta=0
UNET Theta Warmup=0
UNET ZTol=0
UNET ZSATol=0
UNET MxIter=0
UNET MaxInSteps=0
UNET DtIC=0
UNET DtMin=0
UNET MaxCRTS=0
UNET WFStab=0
UNET SFStab=0
UNET WFX=0
UNET SFX=0
UNET DSS MLevel=0
UNET DZMax Abort=0
UNET Convert EG Bridges=0
UNET Use Existing IB Tables=0
UNET Froude Limit=0
UNET Froude Power=0
Write IC File=0
Echo Input=False
Echo Output=False
Write Detailed=0

--- PARKERBR.f01 (steady flow) ---

Flow Title=NFF Regression Equation
Program Version=4.00
Number of Profiles=1
Profile Names=P100yr
River Rch & RM=PARKERBR,Main      ,4805.2
316.9835
River Rch & RM=PARKERBR,Main      ,4469.9
414.7125
River Rch & RM=PARKERBR,Main      ,3578.2
432.3145
River Rch & RM=PARKERBR,Main      ,1477.5
476.5351
River Rch & RM=PARKERBR,Main      ,1181.3
572.5998
River Rch & RM=PARKERBR,Main      ,288.3
579.4121
Boundary for River Rch & Prof#=PARKERBR,Main      ,1
Up Type=0
Dn Type=3
Dn Slope=0.008498

--- PARKERBR.g01 (geometry) ---

Geom Title=Geometry
Program Version=4.00

River Reach=PARKERBR        ,Main
Reach XY= 30
     1605532.225      370581.571     1605489.194      370692.674
     1605486.422      370743.973     1605566.998      370808.245
     1605630.561      371089.824     1605667.846      371160.335
     1605693.891      371271.208     1605908.198      371564.319
     1605968.742      371683.485      1606074.76       371776.97
     1606095.819      371844.047      1606071.64      371957.923
     1606085.679      372087.398     1606227.634      372397.827
     1606272.092      372457.105     1606325.131      372496.883
     1606439.786      372525.742     1606596.816      372599.118
     1606878.821      372660.767     1607038.804      372662.237
     1607167.618      372688.959     1607368.821      372733.546
     1607442.176      372779.083     1607643.119      372991.491
     1607720.499       373133.34     1607913.932      373308.833
     1608076.946      373553.744     1608231.791      373751.448
     1608251.202      373786.573     1608236.959      373918.734

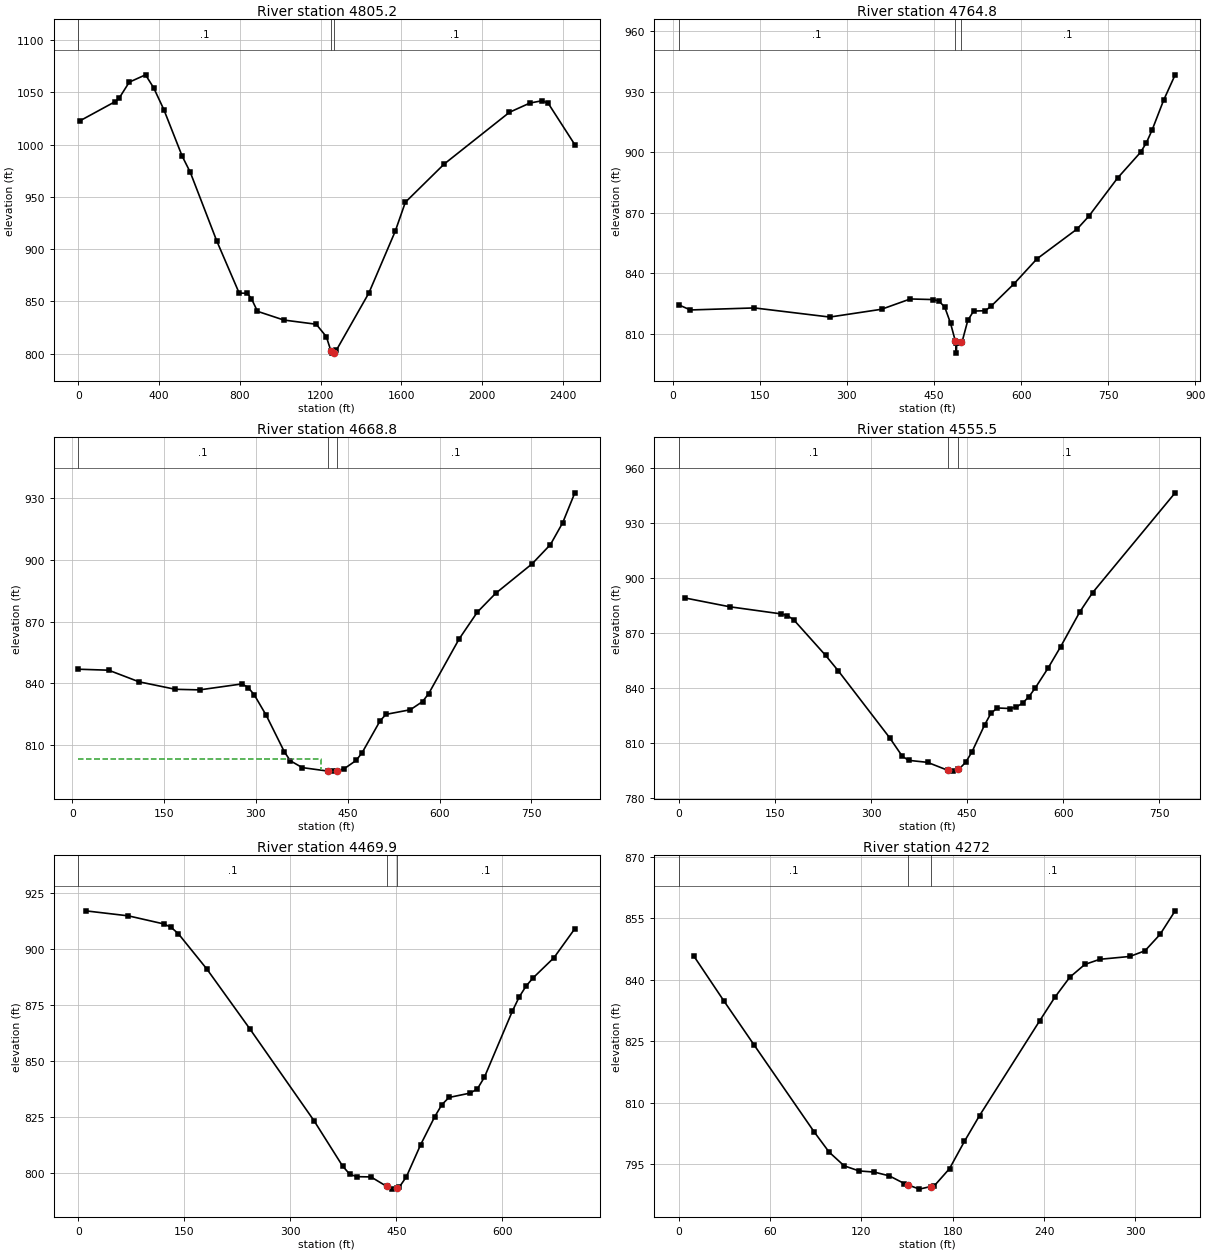
Type RM Length L Ch R = 1 ,4805.2  ,33.9,40.4,45.9
XS GIS Cut Line= 4
     1604953.793      369700.125     1605159.622      370563.524
     1605891.205      370605.773     1606242.109      369842.699
#Sta/Elev= 30
    10.1 1023.08   181.6 1041.11   201.7  1044.4   252.2 1059.82   332.8 1066.84
   373.2  1054.4   423.6 1033.55   514.4  989.04   554.7  973.53   685.9  907.83
   796.8  858.05   837.2  857.75   857.3  852.79   887.6  840.55  1018.1  832.21
  1178.7  828.19  1228.9  816.29  1251.5  802.65    1259  800.55  1266.5     801
  1279.1  803.55  1439.7  858.12  1570.2  917.12  1620.4  944.92  1812.7  981.46
  2136.5 1031.02  2237.7 1039.84  2298.4 1042.05  2328.7 1039.49  2460.3  999.98
#Mann= 3 , 0 , 0
       0      .1       0  1251.5    .045       0  1266.5      .1       0
Bank Sta=1251.5,1266.5
XS Rating Curve= 0 ,0
Exp/Cntr=0.3,0.1

Type RM Length L Ch R = 1 ,4764.8  ,111.6,96,81.3
XS GIS Cut Line= 5
     1605028.833      370608.581     1605259.095      370593.725
      1605457.17      370601.153     1605541.363      370630.633
     1605888.289      370648.182
#Sta/Elev= 30
      10  824.48    30.1  821.91   140.5  822.92   270.4   818.4   359.6  822.26
   409.1  827.36   448.8  827.06   458.7  826.31   468.6  823.24   478.5  815.34
  486.72   806.5  487.83  805.64   488.4  800.53  489.21   805.3   495.9  805.84
   498.3  806.05   508.2  816.73   518.2  821.37     538  821.53   547.9  823.64
   587.6  834.79   627.3  847.21   696.8  862.07   716.7  868.33   766.3  887.27
     806  900.04   815.9   904.7   825.8  911.04   845.7  925.85   865.5  938.39
#Mann= 3 , 0 , 0
      10      .1       0  486.72    .045       0   495.9      .1       0
Bank Sta=486.72,495.9
XS Rating Curve= 0 ,0
Exp/Cntr=0.3,0.1

Type RM Length L Ch R = 1 ,4668.8  ,112.2,113.3,112.9
XS GIS Cut Line= 4
     1605062.258      370738.568     1605389.007      370746.023
     1605564.195      370685.088      1605872.68      370686.992
#Sta/Elev= 30
     9.9  846.88    59.4   846.4   108.9  840.76   168.4   837.1     208  836.83
   277.3  839.73   287.2  837.98   297.1  834.46   316.9  824.36   346.4  806.66
   356.1  802.33   375.6     799     417  797.33   424.5  797.29     432  797.53
     444  798.44   463.5  802.48   473.3  806.22   502.6   821.7   512.3  824.91
   552.1  827.16     572  831.12     582  834.96   631.7  861.55   661.6  874.68
   691.4  883.78   751.1  898.19     781  907.55   800.9  918.11   820.8  932.71
#Mann= 3 , 0 , 0
     9.9      .1       0     417    .045       0     432      .1       0
#XS Ineff= 2 , 0
          405.59  803.18
Permanent Ineff=
       F       F
Bank Sta=417,432
XS Rating Curve= 0 ,0
Exp/Cntr=0.3,0.1

Type RM Length L Ch R = 1 ,4555.5  ,85.5,85.6,87.3
XS GIS Cut Line= 4
     1605132.007      370828.365     1605460.858      370829.702
     1605649.345      370742.811     1605887.294      370745.484
#Sta/Elev= 30
      10  889.04    79.7  884.24   159.4  880.38   169.4  879.45   179.4  877.16
   229.2  857.72   249.1  849.23   328.9  812.85   348.6  802.77   358.5  800.44
   388.2  799.34   420.2  794.95   427.7  794.55   435.2  795.49   437.6  795.79
   447.5  799.29   457.3  804.92   477.1  819.69     487  826.07   496.9  829.02
   516.6  828.72   526.5  829.51   536.4  831.64   546.3  835.17   556.2  839.93
   576.1  850.72   595.9   862.5   625.6   881.4   645.5  891.88   774.4  946.43
#Mann= 3 , 0 , 0
       0      .1       0   420.2    .045       0   435.2      .1       0
Bank Sta=420.2,435.2
XS Rating Curve= 0 ,0
Exp/Cntr=0.3,0.1

Type RM Length L Ch R = 1 ,4469.9  ,197.5,197.9,198.2
XS GIS Cut Line= 4
     1605138.765       370884.72     1605471.951      370900.217
     1605701.825      370827.898     1605828.384      370809.818
#Sta/Elev= 30
    10.1  917.15    70.8   914.9   121.3  911.26   131.4  909.72   141.5   906.9
   181.9  891.08   242.6   864.4   333.5   823.3   373.7  803.15   383.8  799.47
   393.8  798.33   413.9  798.23   436.5  793.95     444  792.77   451.5  793.43
     454  793.65   464.1   798.3   484.2  812.59   504.2  825.15   514.3  830.53
   524.3  833.73   554.4   835.7   564.5  837.57   574.5   842.8   613.9  872.24
   623.7  878.66   633.5  883.56   643.4   887.2   672.9  896.21   702.4  909.16
#Mann= 3 , 0 , 0
       0      .1       0   436.5    .045       0   451.5      .1       0
Bank Sta=436.5,451.5
XS Rating Curve= 0 ,0
Exp/Cntr=0.3,0.1

Type RM Length L Ch R = 1 ,4272    ,269.9,264.9,259.8
XS GIS Cut Line= 2
     1605471.951      371104.262     1605784.475       371011.28
#Sta/Elev= 26
     9.9  845.83    29.6  834.89    49.4  824.15    88.9  802.88    98.8   797.9
   108.7  794.53   118.6  793.28   128.4  793.01   138.3  792.09   148.2  790.21
   150.6  789.88   158.1  788.84   165.6  789.48     168  789.69   177.9  793.84
   187.7  800.51   197.6   806.8   237.1  829.96     247  835.68   256.9  840.62
   266.8  843.75   276.7  845.01   296.4   845.7   306.3  847.09   316.2  851.09
   326.1  856.85
#Mann= 3 , 0 , 0
       0      .1       0   150.6    .045       0   165.6      .1       0
Bank Sta=150.6,165.6
XS Rating Curve= 0 ,0
Exp/Cntr=0.3,0.1

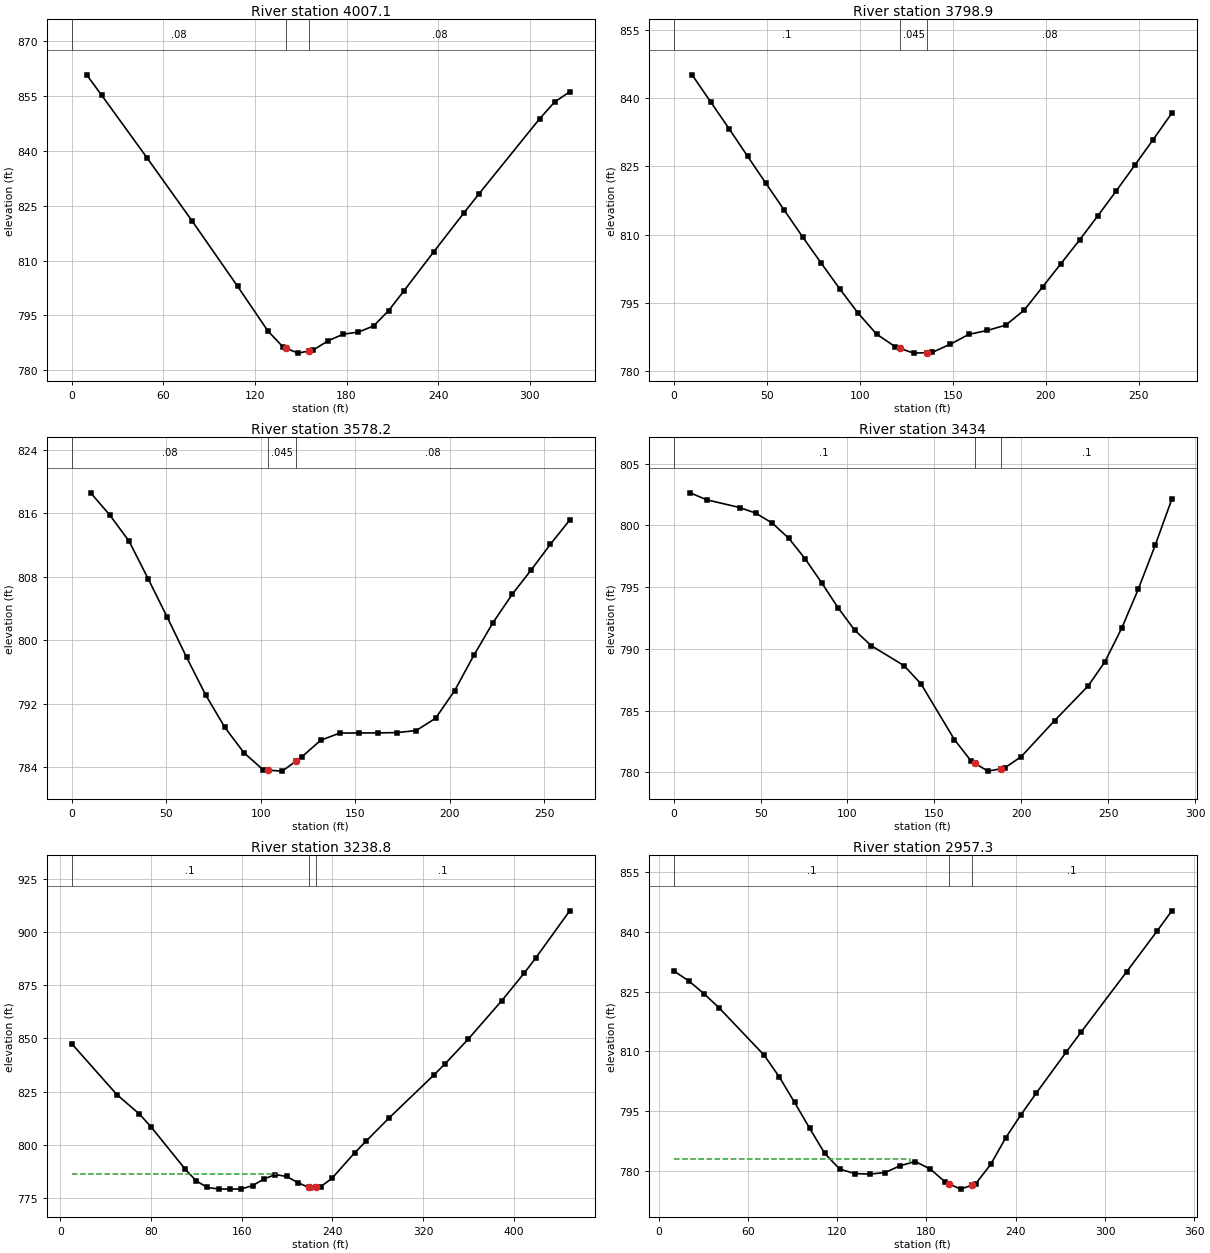
Type RM Length L Ch R = 1 ,4007.1  ,212.2,208.2,204.2
XS GIS Cut Line= 2
     1605575.265      371383.209     1605859.378      371223.073
#Sta/Elev= 23
     9.9  860.85    19.8  855.21    49.4  838.13    79.1  820.73   108.7  802.95
   128.5  790.75   138.4  786.36   140.7  785.96   148.2  784.67   155.7  785.29
   158.1  785.49     168  788.06   177.9  789.86   187.8  790.43   197.7  792.11
   207.5  796.28   217.4  801.62   237.2  812.46     257  823.13   266.8  828.32
   306.4  848.82   316.3  853.44   326.1  856.19
#Mann= 3 , 0 , 0
       0     .08       0   140.7    .045       0   155.7     .08       0
Bank Sta=140.7,155.7
XS Rating Curve= 0 ,0
Exp/Cntr=0.3,0.1

Type RM Length L Ch R = 1 ,3798.9  ,215.7,220.7,225.7
XS GIS Cut Line= 2
     1605730.236      371561.425     1605936.863      371390.958
#Sta/Elev= 29
     9.9  845.08    19.8  839.19    29.8  833.24    39.7  827.23    49.6  821.26
    59.5  815.35    69.4  809.45    79.4  803.71    89.3  798.09    99.2  792.75
   109.1  788.16   119.1   785.4   121.5  785.06     129  783.98   136.5  784.09
   138.9  784.12   148.8  785.94   158.7  788.09   168.7  788.96   178.6  790.13
   188.5  793.42   198.4  798.51   208.3  803.64   218.3  808.83   228.2  814.17
   238.1  819.65     248  825.24   257.9  830.88   267.9  836.67
#Mann= 3 , 0 , 0
       0      .1       0   121.5    .045       0   136.5     .08       0
Bank Sta=121.5,136.5
XS Rating Curve= 0 ,0
Exp/Cntr=0.3,0.1

Type RM Length L Ch R = 1 ,3578.2  ,146.4,144.2,141.6
XS GIS Cut Line= 2
     1605854.212      371708.648     1606089.251      371589.837
#Sta/Elev= 28
    10.1  818.55    20.3  815.73    30.4  812.46    40.5  807.74    50.6  802.89
    60.8  797.86    70.9  793.12      81  789.05    91.2  785.83   101.3   783.7
   103.9  783.65   111.4  783.53   118.9  784.83   121.6  785.29   131.7  787.41
   141.8  788.32   151.9  788.33   162.1  788.34   172.2  788.38   182.3  788.64
   192.5  790.19   202.6  793.67   212.7   798.1   222.8   802.2     233  805.78
   243.1  808.87   253.2  812.08   263.4  815.12
#Mann= 3 , 0 , 0
       0     .08       0   103.9    .045       0   118.9     .08       0
Bank Sta=103.9,118.9
XS Rating Curve= 0 ,0
Exp/Cntr=0.3,0.1

Type RM Length L Ch R = 1 ,3434    ,182.5,195.3,208.3
XS GIS Cut Line= 3
     1605871.098      371806.066     1605993.796       371797.16
     1606130.347      371707.116
#Sta/Elev= 27
     9.5  802.64    18.9  802.08    37.9  801.45    47.3  800.99    56.8  800.18
    66.2  798.96    75.7  797.28    85.2  795.34    94.6  793.32   104.1  791.52
   113.6  790.26   132.6  788.63   142.3  787.16   161.5  782.65   171.1  780.91
   173.2  780.73   180.8  780.09   188.2  780.28   190.4  780.34     200  781.27
   219.2  784.19   238.5     787   248.1  788.95   257.7  791.65   267.3  794.83
     277  798.38   286.6  802.12
#Mann= 3 , 0 , 0
       0      .1       0   173.2    .045       0   188.2      .1       0
Bank Sta=173.2,188.2
XS Rating Curve= 0 ,0
Exp/Cntr=0.3,0.1

Type RM Length L Ch R = 1 ,3238.8  ,290.5,281.5,272.4
XS GIS Cut Line= 2
     1605856.795      371935.938      1606306.21      371941.103
#Sta/Elev= 30
      10  847.54    49.9   823.6    69.9  814.41    79.9  808.56   109.9  788.78
   119.9  783.08   129.8  779.96   139.8  779.25   149.8  779.19   159.8  779.27
   169.8  780.86   179.8     784   189.8  786.02   199.8  785.12   209.7  782.23
  219.04  780.02  220.04  779.55  225.93  780.09   229.7  780.31   239.7  784.27
   259.7  796.23   269.7  801.68   289.6  812.36   329.6  832.77   339.6   838.1
   359.6  849.44   389.5  867.68   409.5  880.75   419.5  887.75   449.4  909.85
#Mann= 3 , 0 , 0
      10      .1       0  219.04    .045       0  225.93      .1       0
#XS Ineff= 2 , 0
          190.01  786.45
Permanent Ineff=
       F       F
Bank Sta=219.04,225.93
XS Rating Curve= 0 ,0
Exp/Cntr=0.3,0.1

Type RM Length L Ch R = 1 ,2957.3  ,171.7,171.4,171.1
XS GIS Cut Line= 2
     1605954.943      372282.039     1606272.633      372147.731
#Sta/Elev= 30
    10.1  830.19    20.3  827.64    30.4  824.48    40.6  820.91      71  808.98
    81.2   803.5    91.3   797.2   101.4  790.73   111.6  784.38   121.7  780.43
   131.9  779.31     142  779.18   152.2  779.58   162.3  781.28   172.5  782.34
   182.6  780.43   192.7  777.16   195.4   776.7   202.9  775.41   210.4  776.38
     213  776.72   223.2  781.63   233.3  788.32   243.5  794.07   253.6  799.41
   273.9  809.79     284  814.86   314.5  829.93   334.8  840.07   344.9  845.25
#Mann= 3 , 0 , 0
    10.1      .1       0   195.4    .045       0   210.4      .1       0
#XS Ineff= 2 , 0
          168.88  782.99
Permanent Ineff=
       F       F
Bank Sta=195.4,210.4
XS Rating Curve= 0 ,0
Exp/Cntr=0.3,0.1

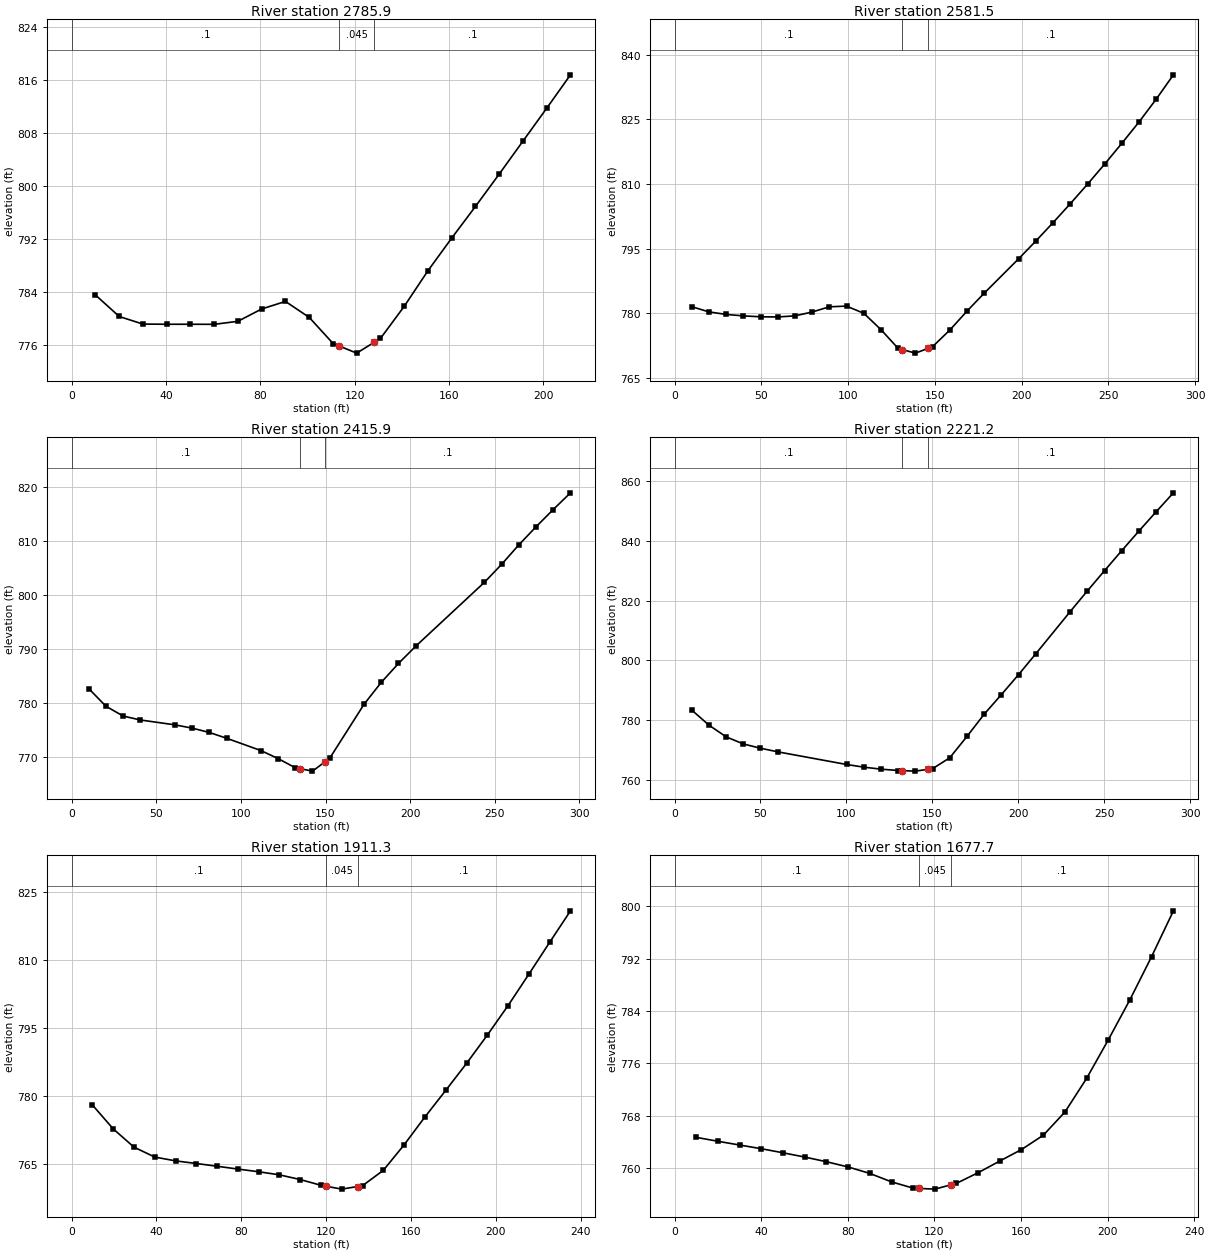
Type RM Length L Ch R = 1 ,2785.9  ,225,204.4,183.7
XS GIS Cut Line= 2
     1606094.417      372411.181      1606288.13      372325.947
#Sta/Elev= 23
    10.1  783.61    20.2  780.37    30.2  779.23    40.3   779.2    50.4   779.2
    60.5  779.19    70.5  779.64    80.6   781.5    90.7  782.64   100.8  780.23
   110.9   776.3   113.4  775.94   120.9  774.85   128.4  776.49     131  777.06
   141.1  781.91   151.2  787.29   161.2  792.17   171.3  796.95   181.4  801.84
   191.5  806.82   201.6  811.79   211.6  816.78
#Mann= 3 , 0 , 0
       0      .1       0   113.4    .045       0   128.4      .1       0
Bank Sta=113.4,128.4
XS Rating Curve= 0 ,0
Exp/Cntr=0.3,0.1

Type RM Length L Ch R = 1 ,2581.5  ,164.9,165.6,166.4
XS GIS Cut Line= 2
     1606311.376      372643.637     1606381.112       372364.69
#Sta/Elev= 30
     9.9  781.51    19.8   780.3    29.7  779.71    39.7  779.37    49.6  779.16
    59.5  779.12    69.4  779.38    79.3  780.27    89.2  781.48    99.1  781.64
   109.1  779.97     119  776.16   128.9   771.8   131.3  771.54   138.8  770.72
   146.3  771.85   148.7  772.22   158.6  776.06   168.6   780.5   178.5  784.66
   198.3  792.63   208.2  796.75   218.1  801.01     228  805.39     238  809.96
   247.9  814.64   257.8  819.46   267.7  824.42   277.6  829.72   287.5  835.36
#Mann= 3 , 0 , 0
       0      .1       0   131.3    .045       0   146.3      .1       0
Bank Sta=131.3,146.3
XS Rating Curve= 0 ,0
Exp/Cntr=0.3,0.1

Type RM Length L Ch R = 1 ,2415.9  ,194.6,194.7,194.8
XS GIS Cut Line= 2
     1606463.637      372690.842     1606544.105      372407.347
#Sta/Elev= 25
    10.2   782.7    20.3  779.46    30.5  777.65    40.6  776.93      61  776.03
    71.1  775.43    81.3  774.63    91.5  773.56   111.8  771.28   121.9  769.81
   132.1  768.11   134.8  767.94   142.3  767.48   149.8  769.22   152.4  769.82
   172.8  779.85   182.9  783.87   193.1  787.37   203.2  790.53   243.9  802.37
     254  805.67   264.2  809.28   274.4  812.63   284.5   815.8   294.7  818.89
#Mann= 3 , 0 , 0
       0      .1       0   134.8    .045       0   149.8      .1       0
Bank Sta=134.8,149.8
XS Rating Curve= 0 ,0
Exp/Cntr=0.3,0.1

Type RM Length L Ch R = 1 ,2221.2  ,311.4,309.8,308.3
XS GIS Cut Line= 2
     1606646.045      372752.091     1606726.113      372473.144
#Sta/Elev= 27
      10  783.34      20  778.31      30  774.39      40  772.01      50  770.57
      60  769.37   100.1  765.13   110.1  764.24   120.1  763.57   130.1  763.12
   132.6  763.07   140.1  762.91   147.6  763.53   150.1  763.73   160.1  767.38
   170.1  774.51   180.1  781.95   190.1   788.5   200.1  795.19   210.2  802.22
   230.2  816.33   240.2  823.26   250.2  830.05   260.2  836.73   270.2   843.3
   280.2  849.74   290.2  856.05
#Mann= 3 , 0 , 0
       0      .1       0   132.6    .045       0   147.6      .1       0
Bank Sta=132.6,147.6
XS Rating Curve= 0 ,0
Exp/Cntr=0.3,0.1

Type RM Length L Ch R = 1 ,1911.3  ,231.4,233.6,235.8
XS GIS Cut Line= 2
     1606962.252      372788.276     1607011.326      372558.403
#Sta/Elev= 26
     9.8  778.03    19.6  772.75    29.4  768.71    39.2  766.52      49  765.68
    58.8   765.1    68.6  764.49    78.4  763.87    88.1  763.28    97.9   762.6
   107.7  761.56   117.5  760.29   119.8  760.09   127.3  759.44   134.8  760.02
   137.1   760.2   146.9  763.59   156.7  769.22   166.5  775.38   176.3  781.24
   186.1   787.2   195.9  793.45   205.7  799.99   215.5  806.92   225.3  813.96
   235.1  820.91
#Mann= 3 , 0 , 0
       0      .1       0   119.8    .045       0   134.8      .1       0
Bank Sta=119.8,134.8
XS Rating Curve= 0 ,0
Exp/Cntr=0.3,0.1

Type RM Length L Ch R = 1 ,1677.7  ,191.5,200.2,209
XS GIS Cut Line= 2
     1607179.211      372827.019     1607248.948      372607.477
#Sta/Elev= 25
      10  764.71      20  764.11      30  763.54    40.1  762.97    50.1  762.35
    60.1   761.7    70.1  760.99    80.1  760.19    90.1  759.21   100.2  757.91
   110.2  756.95   112.7  756.91   120.2   756.8   127.7  757.46   130.2  757.68
   140.2  759.31   150.2  761.09   160.2  762.84   170.3  765.03   180.3  768.58
   190.3  773.71   200.3  779.59   210.3  785.72   220.3   792.3   230.4  799.31
#Mann= 3 , 0 , 0
       0      .1       0   112.7    .045       0   127.7      .1       0
Bank Sta=112.7,127.7
XS Rating Curve= 0 ,0
Exp/Cntr=0.3,0.1

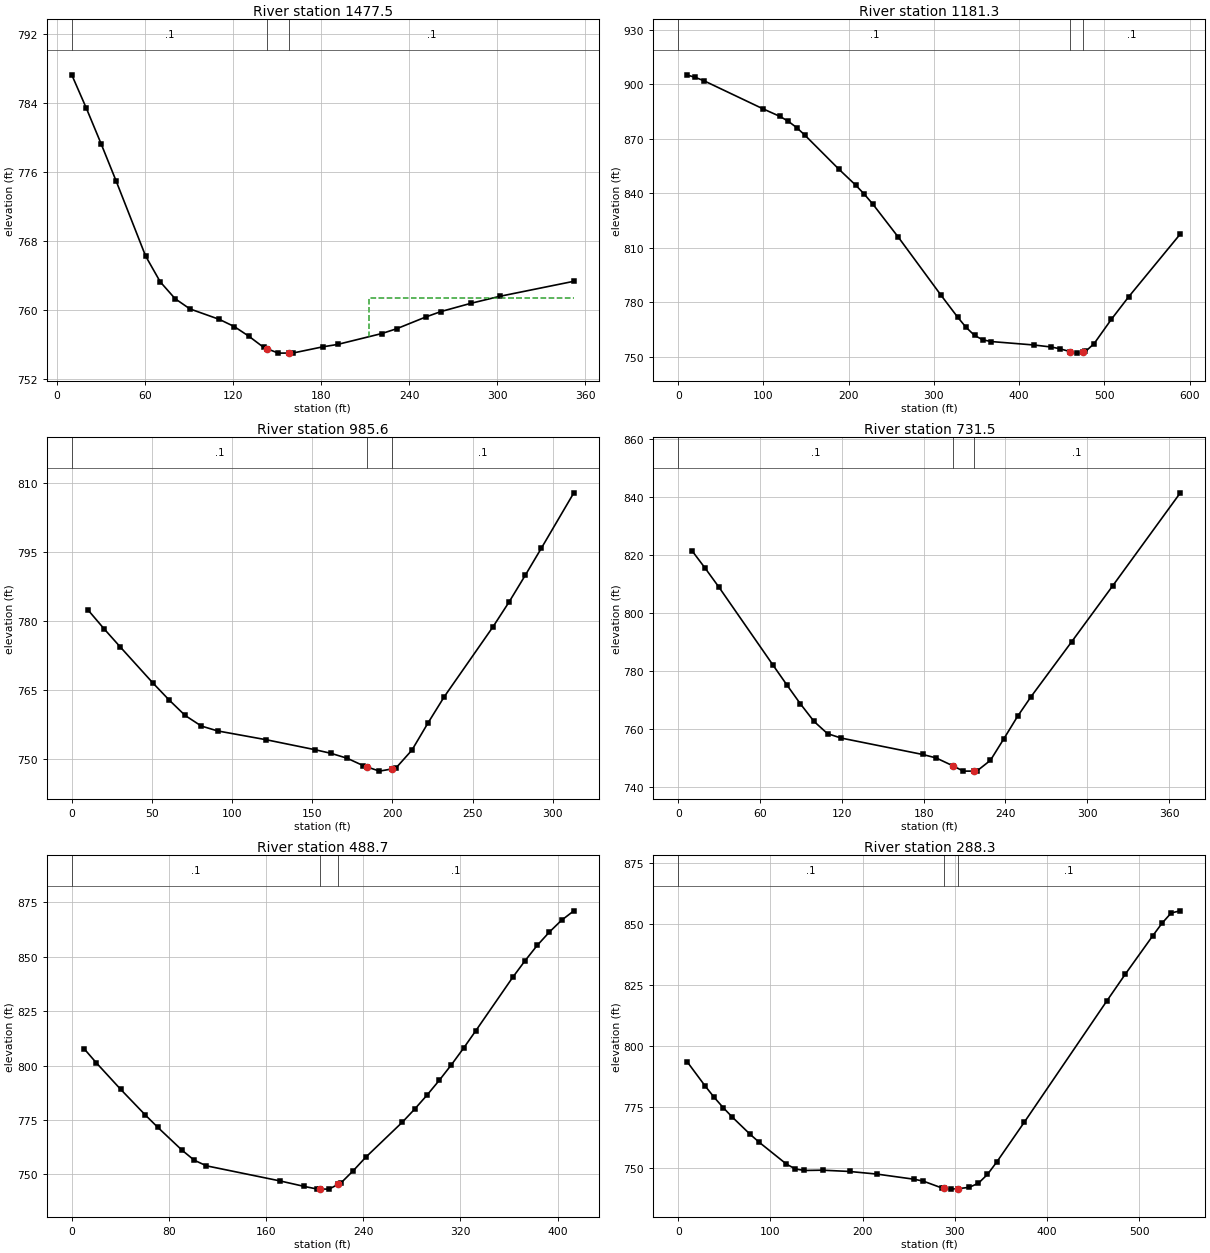
Type RM Length L Ch R = 1 ,1477.5  ,290.2,296.2,302.2
XS GIS Cut Line= 2
     1607297.023       372891.29     1607521.731      372620.091
#Sta/Elev= 25
    10.1   787.3    20.1  783.39    30.2  779.24    40.3  774.97    60.4  766.24
    70.4  763.23    80.5  761.28    90.6  760.09   110.7  758.87   120.8  758.04
   130.8  756.91   140.9  755.61   143.4  755.44   150.9  754.95   158.4  754.96
     161  754.97   181.1  755.68   191.2  755.96   221.4  757.23   231.4  757.78
   251.6  759.17   261.6  759.78   281.8  760.73   301.9  761.56   352.2   763.3
#Mann= 3 , 0 , 0
    10.1      .1       0   143.4    .045       0   158.4      .1       0
#XS Ineff= 2 , 0
                          212.59           761.4
Permanent Ineff=
       F       F
Bank Sta=143.4,158.4
XS Rating Curve= 0 ,0
Exp/Cntr=0.3,0.1

Type RM Length L Ch R = 1 ,1181.3  ,196.6,195.7,194.8
XS GIS Cut Line= 3
     1607173.556      373082.614     1607580.464      372990.536
     1607721.119      372891.483
#Sta/Elev= 30
     9.9  905.09    19.9  903.69    29.8  901.91    99.3  886.43   119.2  882.26
   129.1  879.56   139.1  876.03     149  871.74   188.7  853.12   208.6  844.27
   218.5  839.38   228.5  833.91   258.3   815.8   307.9   784.2   327.8  771.89
   337.7  766.28   347.7   761.8   357.6  759.33   367.5  758.42   417.2  756.54
   437.4  755.44   447.6  754.51   460.3  752.81   467.8  752.06   475.3  752.73
   477.9  752.96     488  757.26   508.3  770.66   528.5  782.97   589.2  817.57
#Mann= 3 , 0 , 0
       0      .1       0   460.3    .045       0   475.3      .1       0
Bank Sta=460.3,475.3
XS Rating Curve= 0 ,0
Exp/Cntr=0.3,0.1

Type RM Length L Ch R = 1 ,985.6   ,254,254.1,254.1
XS GIS Cut Line= 2
     1607561.472      373250.605     1607809.425      373059.475
#Sta/Elev= 25
    10.1  782.45    20.2  778.31    30.3  774.36    50.5  766.57    60.6  762.87
    70.7  759.46    80.8  757.16    90.9   756.1   121.2  754.18   151.5  752.02
   161.6  751.22   171.7  750.15   181.8  748.53   184.4  748.22   191.9  747.34
   199.4   747.8     202  747.96   212.1   751.9   222.2  757.86   232.3  763.55
   262.6  778.73   272.7  784.17   282.8  789.99   292.9  795.93   313.1  807.95
#Mann= 3 , 0 , 0
       0      .1       0   184.4    .045       0   199.4      .1       0
Bank Sta=184.4,199.4
XS Rating Curve= 0 ,0
Exp/Cntr=0.3,0.1

Type RM Length L Ch R = 1 ,731.5   ,240.9,242.9,244.9
XS GIS Cut Line= 2
     1607739.688      373428.821      1608031.55      373204.114
#Sta/Elev= 22
      10  821.64    19.9  815.45    29.9  808.97    69.7  781.96    79.6   775.3
    89.6  768.71    99.6  762.64   109.5  758.41   119.5  756.89   179.2  751.23
   189.1  750.04   201.6  747.28   209.1  745.47   216.6  745.48     219  745.48
     229  749.19   238.9  756.68   248.9  764.37   258.8  771.18   288.7  790.21
   318.6  809.39   368.3  841.57
#Mann= 3 , 0 , 0
       0      .1       0   201.6    .045       0   216.6      .1       0
Bank Sta=201.6,216.6
XS Rating Curve= 0 ,0
Exp/Cntr=0.3,0.1

Type RM Length L Ch R = 1 ,488.7   ,198.5,200.3,202.1
XS GIS Cut Line= 2
     1607871.413      373609.621     1608220.097      373387.496
#Sta/Elev= 30
    10.1   807.8    20.2  801.29    40.3  789.07    60.5  777.34    70.6  771.75
    90.8  761.12   100.8  756.53   110.9  753.94   171.4  747.01   191.6  744.45
   201.7  743.31   204.3  743.29   211.8  743.23   219.3  745.43   221.8  746.16
   231.9  751.77     242  757.86   272.3  774.07   282.3  779.99   292.4  786.37
   302.5  793.18   312.6   800.4   322.7   808.1   332.8  816.14     363  840.53
   373.1  848.12   383.2  855.24   393.3  861.42   403.3  866.83   413.4  871.15
#Mann= 3 , 0 , 0
       0      .1       0   204.3    .045       0   219.3      .1       0
Bank Sta=204.3,219.3
XS Rating Curve= 0 ,0
Exp/Cntr=0.3,0.1

Type RM Length L Ch R = 1 ,288.3   ,273.2,288.3,303.5
XS GIS Cut Line= 3
     1607866.248      373684.523     1608036.715      373728.431
     1608362.154      373555.381
#Sta/Elev= 30
     9.8  793.56    29.3  783.64    39.1  778.99    48.9  774.78    58.7  770.93
    78.2  763.83      88  760.59   117.4  751.69   127.1   749.7   136.9  749.09
   156.5  749.21     186  748.68   215.9  747.59   255.7  745.51   265.7  744.74
   285.6  741.98   288.1  741.84   295.6  741.45   303.1  741.61   315.5  742.18
   325.5  743.83   335.4  747.47   345.4  752.51   375.3  768.82   464.9  818.54
   484.8  829.44   514.7  845.22   524.7  850.34   534.7  854.58   544.6  855.45
#Mann= 3 , 0 , 0
       0      .1       0   288.1    .045       0   303.1      .1       0
Bank Sta=288.1,303.1
XS Rating Curve= 0 ,0
Exp/Cntr=0.3,0.1

Chan Stop Cuts=-1
Use User Specified Reach Order=0